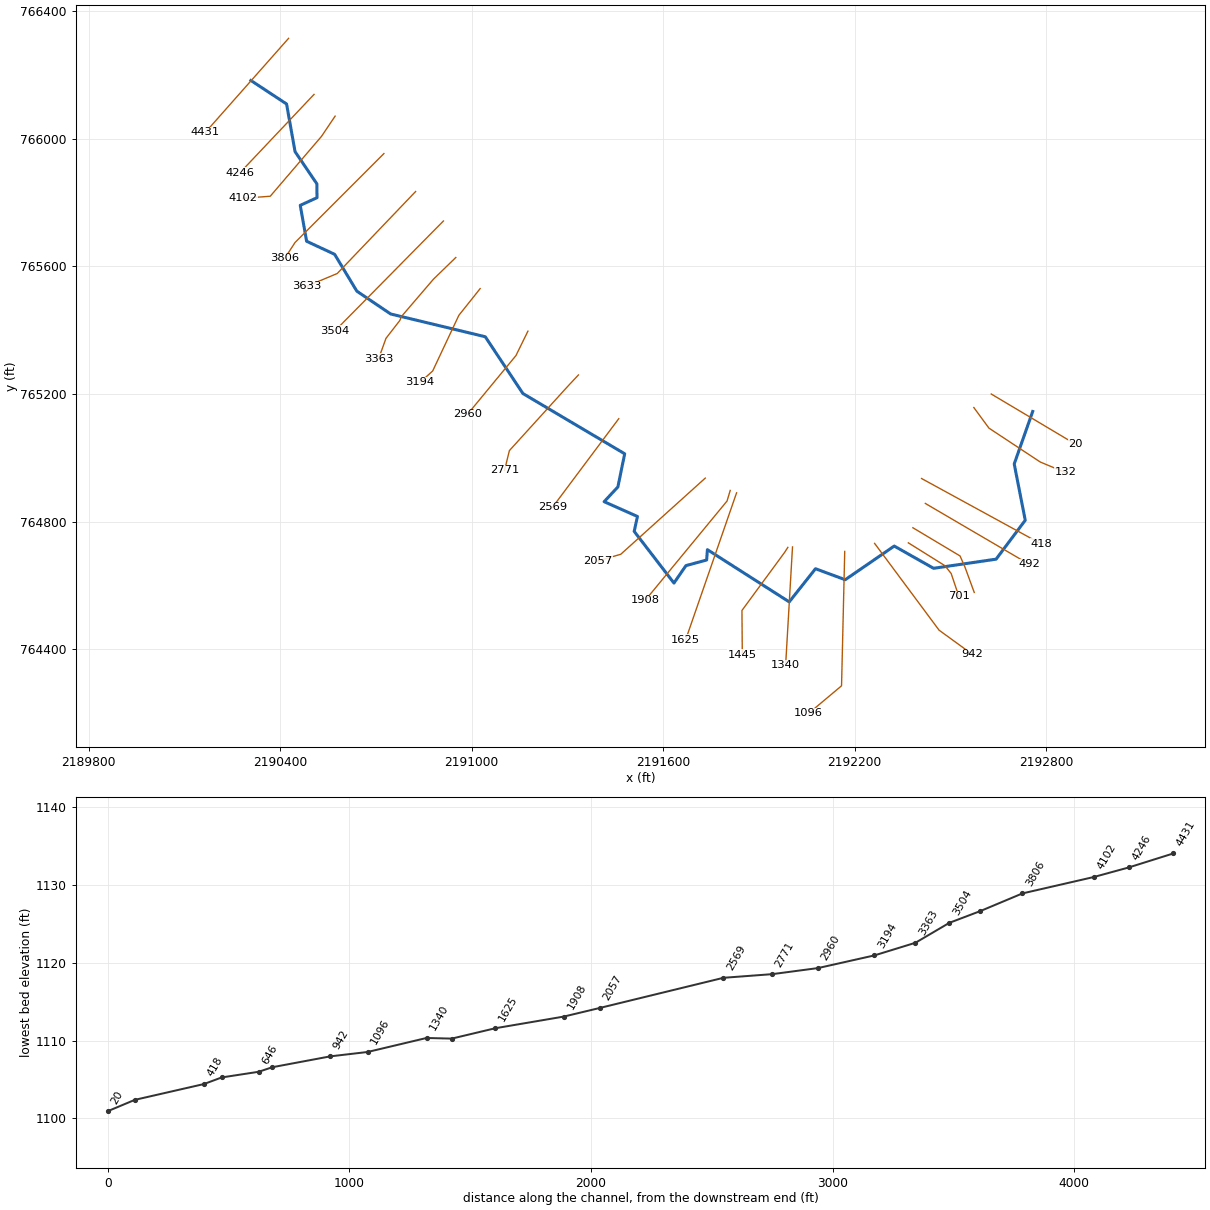
--- CHARITYFK.prj (project) ---

Proj Title=CHARITYFK
Current Plan=p01
Default Exp/Contr=0,0
English Units
Geom File=g01
Flow File=f01
Plan File=p01
BEGIN DESCRIPTION:
---------- MODELED AS PART OF WVEMD CTP PROGRAM, 2023----------
Stream Name: Charity Fork
Flood Zone:  AFH
Upshur County, WV
HEC-RAS Version: RAS 6.3
Vertical Datum: NAVD88
Projection: NAD 1983 StatePlane West Virginia S FIPS 4702 (US Feet)
Terrain: 1-meter LIDAR (FEMA Region III 3DEP collected 2016-2018)
Land Use: 2019 NLCD
Hydrologic Method:
WV SIR2010-5033 regression equations
Additional Model Notes:
None
END DESCRIPTION:
DSS Export Rating Curves= 0
DSS Export Rating Curve Sorted= 0
DSS Export Volume Flow Curves= 0
DXF OffsetX= 0
DXF OffsetY= 0
DXF ScaleX= 0
DXF ScaleY= 0

--- CHARITYFK.p01 (plan) ---

Plan Title=Floodplain
Program Version=6.30
Short Identifier=Floodplain
Geom File=g01
Flow File=f01
Subcritical Flow
K Sum by GR= 0
Std Step Tol= 0.01
Critical Tol= 0.01
Num of Std Step Trials= 20
Max Error Tol= 0.3
Flow Tol Ratio= 0.001
Split Flow NTrial= 30
Split Flow Tol= 0.02
Split Flow Ratio= 0.02
Log Output Level= 0
Friction Slope Method= 1
Unsteady Friction Slope Method= 2
Unsteady Bridges Friction Slope Method= 1
Parabolic Critical Depth
Global Vel Dist= 0 , 0 , 0
Global Log Level= 0
CheckData=False
Encroach Param=-1 ,0,0, 0
Mapping Interval=1HOUR
Computation Time Step Use Courant=        0
Computation Time Step Use Time Series=    0
Computation Time Step Count To Double=0
Computation Time Step Max Doubling=0
Computation Time Step Max Halving=0
Computation Time Step Residence Courant=0
Run HTab= 0
Run UNet= 0
Run Sediment= 0
Run PostProcess= 0
Run WQNet= 0
Run RASMapper=-1
UNET Theta= 0
UNET Theta Warmup= 0
UNET ZTol= 0
UNET ZSATol= 0
UNET MxIter= 0
UNET Max Iter WO Improvement= 0
UNET MaxInSteps= 0
UNET DtIC= 0
UNET DtMin= 0
UNET MaxCRTS= 0
UNET WFStab= 0
UNET SFStab= 0
UNET WFX= 1
UNET SFX= 1
UNET Gravity=32.17405
UNET 1D Methodology=Finite Difference
UNET DSS MLevel= 1
UNET Pardiso=0
UNET DZMax Abort= 0
UNET Use Existing IB Tables= 0
UNET Froude Reduction=False
UNET Froude Limit= 0
UNET Froude Power= 0
UNET D1 Cores= 0
UNET WindReference=Eulerian
UNET WindDragFormulation=Hsu (1988)
UNET D2 Coriolis=0
UNET D2 Cores= 0
UNET D2 Theta= 1
UNET D2 Theta Warmup= 1
UNET D2 Z Tol= 0.01
UNET D2 Volume Tol= 0.01
UNET D2 Max Iterations= 20
UNET D2 Equation= 0
UNET D2 RampUpFraction=0.1
UNET D2 TimeSlices= 1
UNET D2 Turbulence Formulation=Non-Conservative (original)
UNET D2 Eddy Viscosity=0.3
UNET D2 Transverse Eddy Viscosity=0.1
UNET D2 Smagorinsky Mixing=0
UNET D2 BCVolumeCheck=0
UNET D2 Cores=0
UNET D2 SolverType=PARDISO (Direct)
UNET D2 Minimum Iterations= 3
UNET D2 Maximum Iterations= 30
UNET D2 Restart Number= 10
UNET D2 Relaxation Coeff=1.3
UNET D2 SOR Precondition Iterations= 10
UNET D2 ILUT Maximum Fill= 8
UNET D2 ILUT Tolerance=1E-08
UNET D2 Convergence Tolerance=0.00001
UNET D1D2 MaxIter= 0
UNET D1D2 ZTol=0.01
UNET D1D2 QTol=0.1
UNET D1D2 MinQTol=1
Write IC File= 0
Write IC File at Fixed DateTime=0
Write IC File at Sim End=0
Echo Input=False
Echo Parameters=False
Echo Output=False
Write Detailed= 0
HDF Write Warmup=0
HDF Write Time Slices=0
HDF Flush=0
HDF Compression= 1
HDF Chunk Size= 1
HDF Spatial Parts= 1
HDF Use Max Rows=0
HDF Fixed Rows= 1
Calibration Method= 0
Calibration Iterations= 20
Calibration Max Change=0.05
Calibration Tolerance=0.2
Calibration Maximum=1.5
Calibration Minimum=0.5
Calibration Optimization Method= 1
WQ AD Non Conservative
WQ ULTIMATE=-1
WQ Max Comp Step=1HOUR
WQ Output Interval=15MIN
WQ Output Selected Increments= 0
WQ Output face flow=0
WQ Output face velocity=0
WQ Output face area=0
WQ Output face dispersion=0
WQ Output cell volume=0
WQ Output cell surface area=0
WQ Output cell continuity=0
WQ Output cumulative cell continuity=0
WQ Output face conc=0
WQ Output face dconc_dx=0
WQ Output face courant=0
WQ Output face peclet=0
WQ Output face adv mass=0
WQ Output face disp mass=0
WQ Output cell mass=0
WQ Output cell source sink temp=0
WQ Output nsm pathways=0
WQ Output nsm derived pathways=0
WQ Create Restart=0
WQ Fixed Restart=0
WQ System Summary=0
WQ Write To DSS=0
Sorting and Armoring Iterations= 10
XS Update Threshold= 0.02
Bed Roughness Predictor= 0
Hydraulics Update Threshold= 0.02
Energy Slope Method= 1
Volume Change Method= 1
Sediment Retention Method= 0
Sediment TS Multiplier= 1
Warm Up Method= 0
XS Weighting Method= 0
Number of US Weighted Cross Sections= 1
Number of DS Weighted Cross Sections= 1
Upstream XS Weight=0
Main XS Weight=1
Downstream XS Weight=0
Number of DS XS's Weighted with US Boundary= 1
Upstream Boundary Weight= 1
Weight of XSs Associated with US Boundary= 0
Number of US XS's Weighted with DS Boundary= 1
Downstream Boundary Weight= 0.5
Weight of XSs Associated with DS Boundary= 0.5
Percentile Method= 0
Sediment Output Level= 3
Mass or Volume Output= 0
Output Increment Type= 1
Profile and TS Output Increment= 1
Transport Output Increment 1
XS Output Flag= 0
XS Output Increment= 10
Read HDF5 Sediment Hotstart= 0
Sediment Hotstart Type= 0
Write Gradation File= 0
Read Gradation Hotstart= 0
Write HDF5 File= 1
Write Binary Output= 1
Write DSS Sediment File= 0
DSS Sediment Output Type= 1
SV Curve= 0
Specific Gage Flag= 0
Subcell Erosion Methods= 0
Subcell Deposition Methods= 0
Advection Scheme= 1
Matrix Solver= 0
Implicit Weighting Factor= 1
Maximum Outer Loop Convergence Iterations= 5
Convergence Maximum Absolute= 0.001
Convergence RMSE= 0.0001
Grain Fractions Max Abs Error= 0.001
Max Subgrid Regions= 1
Max Subgrid Length Scale= 3.402823E+38
Initial Layer Thickness= 3.402823E+38
Min Layer Thickness= 3.402823E+38
Max Layer Thickness= 3.402823E+38
Number of Layers= 5

--- CHARITYFK.f01 (steady flow) ---

Flow Title=Flows
Program Version=6.31
Number of Profiles= 1
Profile Names=01pct
River Rch & RM=CHARITYFK,Main,4431
     657
River Rch & RM=CHARITYFK,Main,942
     814
Boundary for River Rch & Prof#=CHARITYFK,Main            , 1
Up Type= 0
Dn Type= 3
Dn Slope=0.0136
DSS Import GetInterval= 0
DSS Import GetPeak= 0
DSS Import FillOption= 0

--- CHARITYFK.g01 (geometry) ---

Geom Title=Geometry
Program Version=6.31

River Reach=CHARITYFK       ,Main
Reach XY= 30
2190308.82599007766182.4982466492190420.53617823766108.937161811
 2190447.1180502765959.609586942     2190515.435       765858.81
     2190515.979       765815.37      2190463.41       765791.39
     2190483.356      765678.841     2190571.094      765637.977
     2190640.718       765522.51     2190746.713      765451.026
     2191043.007      765379.743     2191161.078      765201.778
     2191479.865      765013.081     2191458.574      764909.175
     2191415.506      764862.988     2191519.927      764816.658
     2191509.626      764770.042     2191634.193      764608.016
     2191671.766      764662.702     2191736.582      764680.272
     2191739.043      764712.666     2191995.389      764549.066
     2192077.661      764652.944     2192170.836      764618.518
     2192324.391       764723.97     2192447.614      764654.289
      2192643.55      764682.934     2192734.836      764804.754
     2192700.268      764981.2312192758.15054238765145.569042517

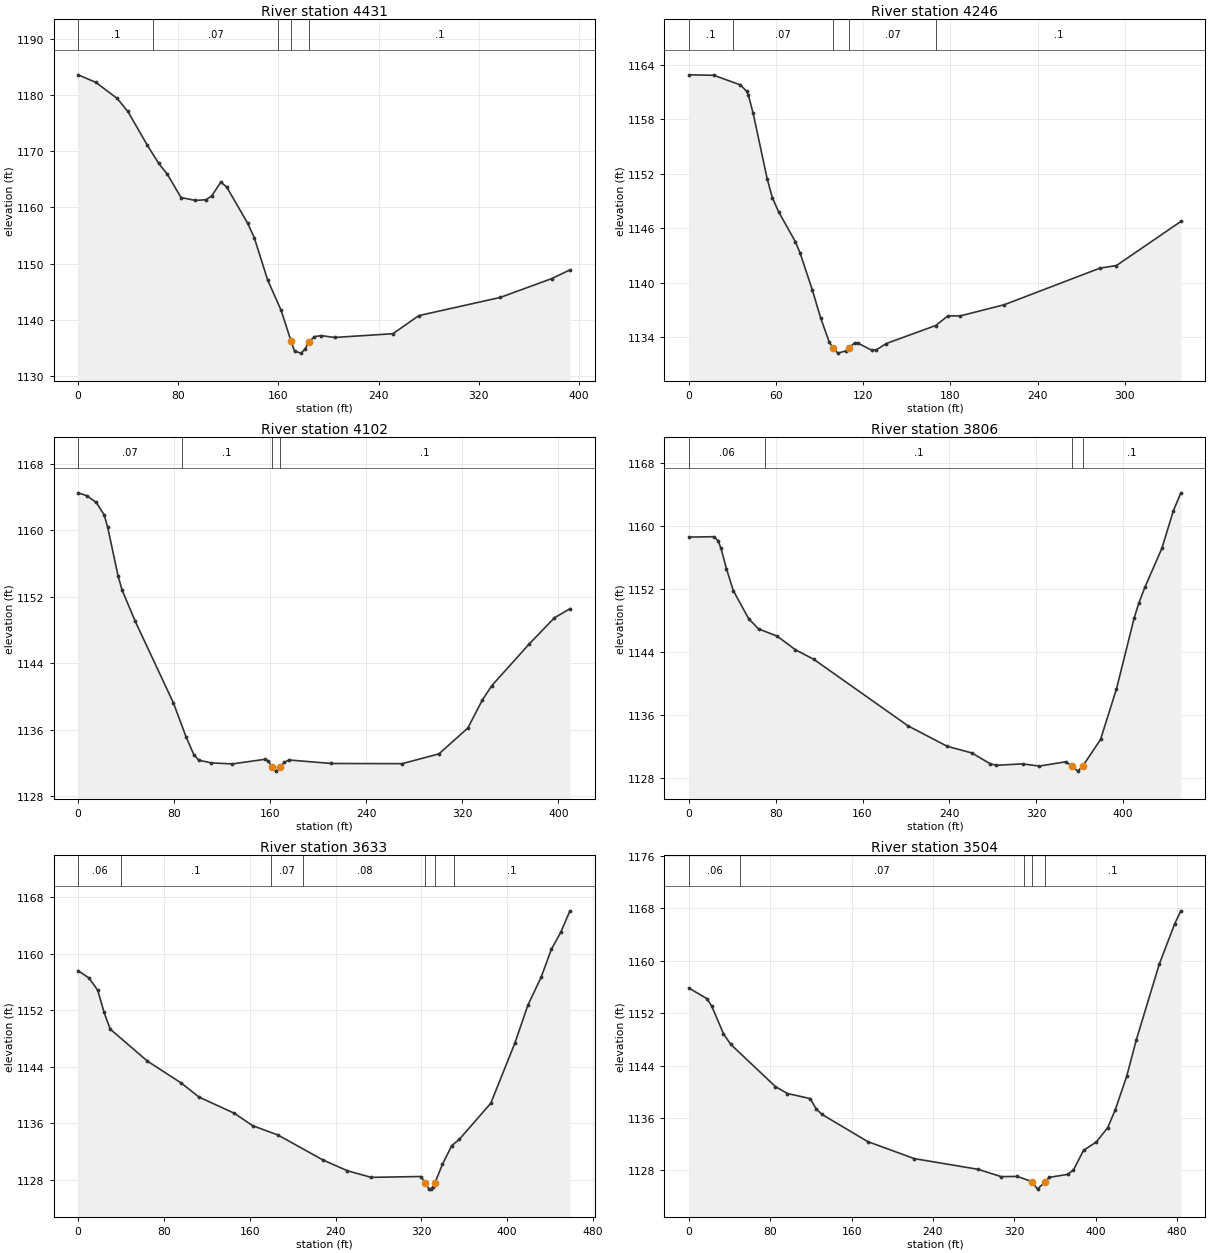
Type RM Length L Ch R = 1 ,4431    ,185.6,185.6,185.6
XS GIS Cut Line= 2
2190426.87067718 766314.570903112190166.45538465766020.322127684
#Sta/Elev= 30
       0 1183.63    14.2 1182.28    31.2 1179.42    39.7 1177.11    55.3 1171.08
    64.4 1167.84    71.3  1165.9    82.2 1161.77    93.6 1161.25   102.1 1161.37
   106.7 1162.05     114 1164.52   118.7 1163.64   135.4 1157.19   140.7 1154.62
   151.4 1147.08   162.1  1141.7   170.1 1136.17   172.9 1134.39   178.1 1134.04
   181.4  1134.8   184.3 1136.05   188.8 1136.98   194.2 1137.16   204.8 1136.83
   251.5  1137.5   272.1 1140.72   337.3 1143.97   378.3 1147.32   392.9 1148.87
#Mann= 5 ,-1,0
       0      .1       0      60     .07       0     160      .1       0
   170.1    .045       0   184.3      .1       0
Bank Sta=170.1,184.3
XS Rating Curve= 0 ,0
Exp/Cntr(USF)=0,0
Exp/Cntr=0.3,0.1

Type RM Length L Ch R = 1 ,4246    ,187.5,143.6,187.5
XS GIS Cut Line= 2
2190506.57456221766138.8925276982190273.84121021765892.830833961
#Sta/Elev= 30
       0 1162.88    17.1 1162.83    35.4 1161.77    39.7 1161.07    40.9 1160.65
    44.2 1158.64    53.8 1151.46    57.4 1149.35    61.7  1147.8    73.3 1144.49
    76.5 1143.26      85 1139.16    90.6 1136.14    96.6 1133.44    99.1 1132.84
   102.5 1132.23   108.3 1132.49  110.38 1132.83   114.1 1133.37   116.1 1133.35
   125.7 1132.56     129 1132.59   135.9 1133.29   169.9 1135.27   178.3 1136.33
   186.8 1136.33   217.1 1137.56     283 1141.59   294.4 1141.88   338.7 1146.73
#Mann= 5 ,-1,0
       0      .1       0      30     .07       0    99.1    .045       0
  110.38     .07       0     170      .1       0
Bank Sta=99.1,110.38
XS Rating Curve= 0 ,0
Exp/Cntr(USF)=0,0
Exp/Cntr=0.3,0.1

Type RM Length L Ch R = 1 ,4102    ,295.8,295.8,295.8
XS GIS Cut Line= 4
2190572.62954544766070.8363124482190529.83266366766007.217157727
2190369.43938568765819.933911619 2190283.3401354765813.349729237
#Sta/Elev= 30
       0 1164.52     7.3 1164.17    15.1 1163.36    21.7 1161.86    24.6 1160.38
    33.2 1154.56    36.6 1152.81    47.6 1149.04    79.4 1139.21    89.9 1135.13
    96.3 1133.01   100.4 1132.33     111    1132   128.4 1131.88   155.9 1132.44
   158.4 1132.23   161.6 1131.48   164.4 1131.01   168.31131.466   171.5 1132.06
   175.7 1132.35     211 1131.93   269.9 1131.91   300.5 1133.09   324.5 1136.19
   336.6 1139.57   344.6 1141.32   375.4 1146.28   396.7 1149.48   409.6 1150.56
#Mann= 4 ,-1,0
       0     .07       0   86.67      .1       0   161.6    .045       0
   168.3      .1       0
Bank Sta=161.6,168.3
XS Rating Curve= 0 ,0
Exp/Cntr(USF)=0,0
Exp/Cntr=0.3,0.1

Type RM Length L Ch R = 1 ,3806    ,172.3,173.6,172.8
XS GIS Cut Line= 3
 2190725.5182365  765953.58242232190446.99076243765674.822105804
2190414.64236728765625.047492712
#Sta/Elev= 30
       0 1158.61    23.2 1158.66    26.7 1158.16    29.5  1157.2    34.5 1154.61
    40.8 1151.83      55 1148.25    64.2 1146.95    81.1 1146.05    98.1 1144.31
   115.1 1143.09   202.1 1134.63   238.1 1132.05   260.7 1131.21   277.6 1129.84
   283.3 1129.64   307.5 1129.82   322.9 1129.54   347.1 1130.08   352.8 1129.59
   358.4  1128.9   363.3 1129.61   379.4 1132.92   394.1 1139.35   410.3 1148.29
   414.6  1150.2   420.4 1152.29   435.9 1157.17   446.4  1161.9   453.4 1164.23
#Mann= 4 ,-1,0
       0     .06       0      70      .1       0   352.8    .045       0
   363.3      .1       0
Bank Sta=352.8,363.3
XS Rating Curve= 0 ,0
Exp/Cntr(USF)=0,0
Exp/Cntr=0.3,0.1

Type RM Length L Ch R = 1 ,3633    ,127.3,128.9,127.8
XS GIS Cut Line= 3
2190824.83928738765834.6751403682190579.22669038765577.776310342
2190484.15040934 765537.98648367
#Sta/Elev= 30
       0  1157.6      10  1156.6    18.3 1154.83    24.2 1151.69    29.9 1149.33
    64.6 1144.79    96.1 1141.69   112.7 1139.69   145.7 1137.39   162.6 1135.64
   186.2 1134.32   227.9  1130.8   251.1 1129.24   273.2 1128.31   319.3 1128.43
   323.61127.542   326.9 1126.69   328.6 1126.64   330.9 1126.92   332.61127.526
   339.6 1130.16   348.3  1132.8   355.4 1133.71   384.7 1138.82   407.1 1147.33
   419.4 1152.78   431.6 1156.67   441.1 1160.63   449.8 1163.03   458.5  1166.1
#Mann= 7 ,-1,0
       0     .06       0      40      .1       0     180     .07       0
     210     .08       0   323.6    .045       0   332.6     .08       0
     350      .1       0
Bank Sta=323.6,332.6
XS Rating Curve= 0 ,0
Exp/Cntr(USF)=0,0
Exp/Cntr=0.3,0.1

Type RM Length L Ch R = 1 ,3504    ,134.1,140.3,141.5
XS GIS Cut Line= 2
2190911.97848826765742.3515541832190571.96665532765398.006087574
#Sta/Elev= 30
       0 1155.84    17.7 1154.22    22.5 1153.04    33.9 1148.87      41 1147.25
    85.1 1140.78    96.9 1139.73   119.3 1138.95   125.1 1137.38   130.7 1136.55
   175.9 1132.38   221.7 1129.78   284.4 1128.15   307.1 1127.03   323.1 1127.06
   337.41126.271   342.9 1125.12   350.2 1126.21   354.3 1126.91   372.7 1127.38
   378.3 1128.06   388.2 1131.05   400.8 1132.33     412 1134.52   419.3  1137.2
   430.6 1142.34   440.1 1147.92   462.6 1159.45   477.9 1165.67   483.9 1167.64
#Mann= 5 ,-1,0
       0     .06       0      50     .07       0     330      .1       0
   337.4    .045       0   350.2      .1       0
Bank Sta=337.4,350.2
XS Rating Curve= 0 ,0
Exp/Cntr(USF)=0,0
Exp/Cntr=0.3,0.1

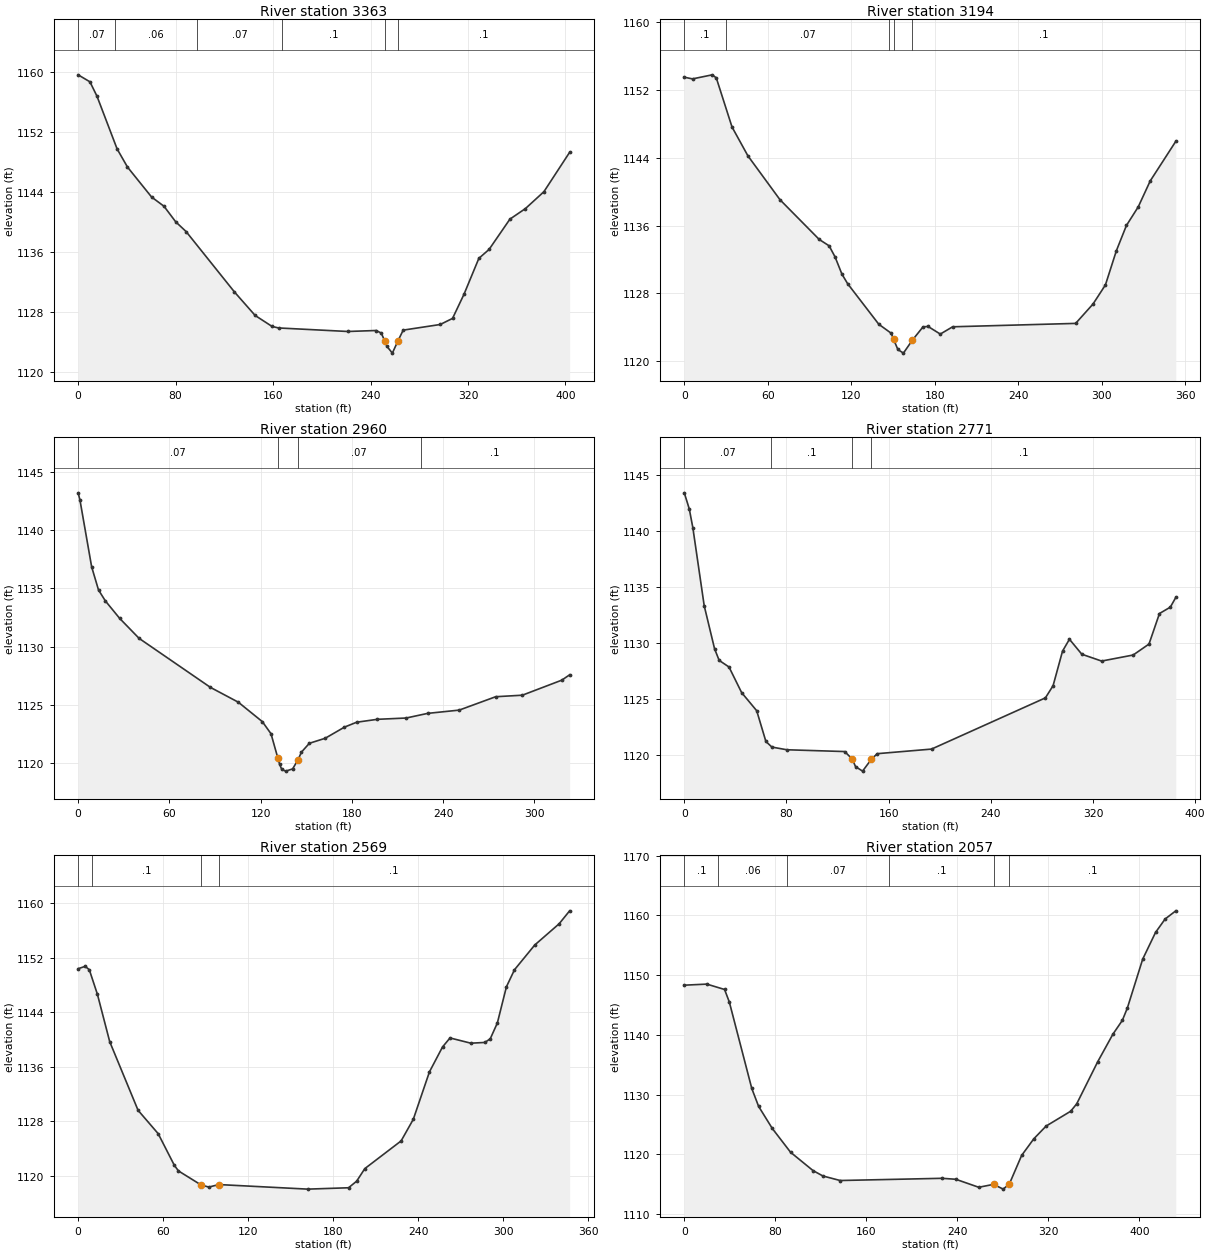
Type RM Length L Ch R = 1 ,3363    ,167.8,169.5,168.5
XS GIS Cut Line= 6
2190950.71687583765627.9455383432190880.65981061765559.896296279
2190781.22622819765443.9609703922190774.87940378 765429.99795669
2190731.99345601765374.7262848522190708.99275851765311.032045631
#Sta/Elev= 30
       0 1159.59     9.7 1158.66    15.5 1156.74      32 1149.73    40.5 1147.32
    60.3 1143.33    70.5  1142.1    80.1 1140.03    88.6 1138.74   128.3  1130.7
   145.3 1127.57   159.2 1126.11   164.5 1125.91   221.3 1125.44   244.6 1125.57
   248.8 1125.23   251.61124.204   253.5 1123.45   257.9 1122.56   262.6 1124.22
   266.8 1125.62   297.2 1126.37   307.3 1127.18   316.7 1130.39   328.9 1135.17
   337.3 1136.36   354.4 1140.39   367.1 1141.79   382.3 1144.04   403.4 1149.28
#Mann= 6 ,-1,0
       0     .07       0      30     .06       0   97.67     .07       0
  167.67      .1       0   251.6    .045       0   262.6      .1       0
Bank Sta=251.6,262.6
XS Rating Curve= 0 ,0
Exp/Cntr(USF)=0,0
Exp/Cntr=0.3,0.1

Type RM Length L Ch R = 1 ,3194    ,234.1,233.7,228.6
XS GIS Cut Line= 4
2191027.10233972765530.5205128832190960.31549326765446.798289506
2190878.30916027765272.4353096372190838.50026075765236.607300075
#Sta/Elev= 30
       0 1153.52     5.9 1153.32    20.1  1153.8      23 1153.44    34.3 1147.64
    45.7 1144.24    68.8 1139.05      97 1134.36   104.1 1133.61   108.4 1132.29
   113.3 1130.27   117.4 1129.14   139.8 1124.35   148.7 1123.29   150.41122.587
   153.5 1121.37   157.5 1120.94     1641122.484   171.6 1124.04   175.2 1124.09
     184 1123.19   192.9 1124.05   281.3 1124.45   293.8 1126.74   302.7 1128.99
   310.6 1133.04   317.8 1136.01   326.3 1138.21   334.9 1141.27   353.3 1145.95
#Mann= 5 ,-1,0
       0      .1       0      30     .07       0   147.1      .1       0
   150.4    .045       0     164      .1       0
Bank Sta=150.4,164
XS Rating Curve= 0 ,0
Exp/Cntr(USF)=0,0
Exp/Cntr=0.3,0.1

Type RM Length L Ch R = 1 ,2960    ,189.5,189.5,188.3
XS GIS Cut Line= 3
2191176.69239195765397.2094956922191139.23865813765320.803878693
 2190987.7924663765137.164656793
#Sta/Elev= 30
       0 1143.21     1.2  1142.6     8.9 1136.85    13.4 1134.87    17.9 1133.93
    27.3 1132.43    40.1 1130.71      87  1126.5   105.3 1125.23   121.1 1123.56
   126.8 1122.52   131.3 1120.43   132.5 1119.88   133.9 1119.45   136.5 1119.31
     141  1119.5   144.51120.272   146.8 1120.94     152  1121.7   162.4 1122.13
   175.1 1123.09   183.1 1123.51   196.8 1123.76   215.6 1123.87   229.8 1124.27
   250.5 1124.55   274.5  1125.7     292 1125.83   317.9 1127.12   323.1 1127.58
#Mann= 4 ,-1,0
       0     .07       0   131.3    .045       0   144.5     .07       0
  225.09      .1       0
Bank Sta=131.3,144.5
XS Rating Curve= 0 ,0
Exp/Cntr(USF)=0,0
Exp/Cntr=0.3,0.1

Type RM Length L Ch R = 1 ,2771    ,200,201.9,202.5
XS GIS Cut Line= 4
2191334.86700063765259.9730223672191302.10247428765225.024194262
2191118.62112673 765022.976281782191103.33101443764960.723681718
#Sta/Elev= 30
       0 1143.41     3.9 1141.97     6.7 1140.29    15.6 1133.31    23.7 1129.47
    27.3 1128.43      35 1127.84    44.9 1125.55    56.7 1123.93    63.9 1121.18
    68.6 1120.68    80.3 1120.44   125.6 1120.28   131.6  1119.6   134.1 1118.93
   139.6 1118.53   146.5 1119.59   151.1 1120.09   193.6  1120.5   282.8 1125.08
   288.8 1126.17   296.2 1129.26   301.6 1130.32   311.3 1128.98   326.8 1128.37
   351.5 1128.91   363.9 1129.89   372.1 1132.62   380.6 1133.19   384.9 1134.06
#Mann= 4 ,-1,0
       0     .07       0   67.91      .1       0   131.6    .045       0
   146.5      .1       0
Bank Sta=131.6,146.5
XS Rating Curve= 0 ,0
Exp/Cntr(USF)=0,0
Exp/Cntr=0.3,0.1

Type RM Length L Ch R = 1 ,2569    ,495,511.3,494.1
XS GIS Cut Line= 2
  2191461.340769765123.0481641072191253.65799469764845.367740944
#Sta/Elev= 30
       0 1150.38       5 1150.73     7.9 1150.23    13.6 1146.64    22.3 1139.68
    42.3 1129.62    56.5 1126.19    67.9 1121.55    70.8 1120.73    86.71118.679
    92.2 1118.36    99.3 1118.73     162 1118.06   190.8 1118.26   196.5 1119.22
   202.3 1121.07   227.9 1125.13   236.5  1128.3   247.9 1135.26   257.1  1138.9
   262.4 1140.23   277.1 1139.46     287 1139.57   290.8 1140.11   295.8 1142.42
   302.2 1147.73   307.9 1150.23   322.2 1153.86   339.4 1156.97   346.8 1158.87
#Mann= 4 ,-1,0
       0     .06       0      10      .1       0    86.7    .045       0
    99.3      .1       0
Bank Sta=86.7,99.3
XS Rating Curve= 0 ,0
Exp/Cntr(USF)=0,0
Exp/Cntr=0.3,0.1

Type RM Length L Ch R = 1 ,2057    ,147,149.3,150.2
XS GIS Cut Line= 3
2191732.40078213764936.9049546412191467.66349064764698.304064164
2191395.08352939764676.971567745
#Sta/Elev= 30
       0 1148.31    19.8 1148.49    35.4 1147.59    39.6 1145.48    59.3 1131.04
    65.3 1128.04    77.3 1124.35    93.4 1120.36   113.1  1117.3   121.8 1116.39
     137 1115.63   226.5    1116   238.6 1115.84   258.8  1114.5   271.81114.985
   280.3 1114.19   285.7 1115.05   296.5 1119.83   307.2 1122.61     318 1124.74
   339.6 1127.22   344.9 1128.46   363.3 1135.48   376.7 1140.11     385 1142.42
   389.4 1144.48   402.9 1152.67   414.2 1157.14   422.6 1159.38     432 1160.75
#Mann= 6 ,-1,0
       0      .1       0      30     .06       0      90     .07       0
     180      .1       0   271.8    .045       0   285.7      .1       0
Bank Sta=271.8,285.7
XS Rating Curve= 0 ,0
Exp/Cntr(USF)=0,0
Exp/Cntr=0.3,0.1

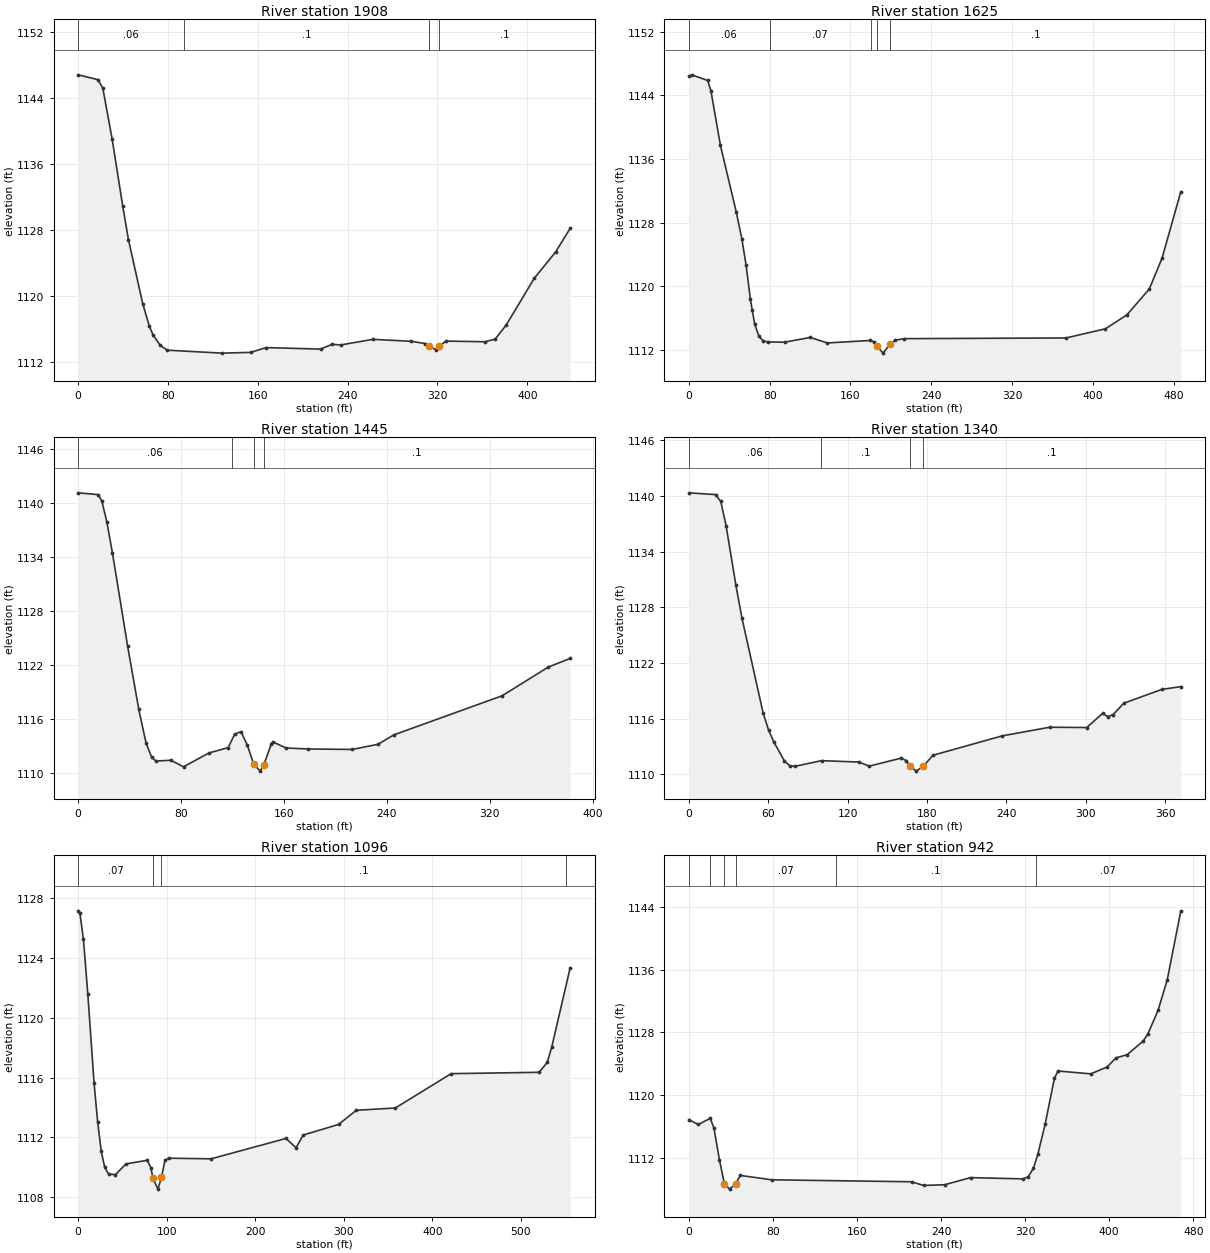
Type RM Length L Ch R = 1 ,1908    ,265.3,283.8,267.3
XS GIS Cut Line= 3
2191810.49403017764898.2214561642191800.58683909764865.129008242
2191543.91694271764553.581296375
#Sta/Elev= 30
       0 1146.83    17.8 1146.24      22 1145.19    30.3 1139.03    39.7 1130.92
    44.8 1126.84    57.5 1119.09    63.2 1116.43    66.6 1115.31    72.9 1114.06
    79.2 1113.44   127.8 1113.08   153.7 1113.17   167.3 1113.75   215.9 1113.57
   226.2 1114.15   233.7 1114.07   262.5 1114.75   296.2 1114.52   309.2 1114.24
   312.31113.911     319 1113.49   321.8  1113.9   327.5 1114.54   362.3 1114.46
   371.4 1114.78   381.2 1116.48   406.3 1122.17   425.2 1125.34   438.2 1128.21
#Mann= 4 ,-1,0
       0     .06       0   94.54      .1       0   312.3    .045       0
   321.8      .1       0
Bank Sta=312.3,321.8
XS Rating Curve= 0 ,0
Exp/Cntr(USF)=0,0
Exp/Cntr=0.3,0.1

Type RM Length L Ch R = 1 ,1625    ,182.3,179.8,175
XS GIS Cut Line= 2
2191830.42502736764890.7473322172191670.97704981764430.673480353
#Sta/Elev= 30
       0 1146.43       3 1146.59    18.6 1145.88    21.9 1144.59    31.3 1137.72
      47 1129.32    52.5 1125.96    56.7 1122.65    60.9 1118.43    62.7 1117.05
    65.2 1115.24    69.4 1113.69    73.6 1113.12    78.5 1112.99    94.8 1112.96
   120.2 1113.55   137.1 1112.86   179.5 1113.17   183.7 1112.99   185.8 1112.48
   192.2 1111.58   199.21112.713   204.2 1113.21   213.3  1113.4   373.3 1113.49
   412.3 1114.64   433.5 1116.39   455.7 1119.65   468.3 1123.51   486.9 1131.89
#Mann= 5 ,-1,0
       0     .06       0      80     .07       0     180      .1       0
   185.8    .045       0   199.2      .1       0
Bank Sta=185.8,199.2
XS Rating Curve= 0 ,0
Exp/Cntr(USF)=0,0
Exp/Cntr=0.3,0.1

Type RM Length L Ch R = 1 ,1445    ,98.5,104.6,112.6
XS GIS Cut Line= 4
2191991.02353243764719.8279511842191980.57608484764703.634407423
2191847.26665362 764522.266717292191848.33106591764384.204400544
#Sta/Elev= 30
       0 1141.17    15.6 1140.97    18.4 1140.26    22.3 1137.95    26.7 1134.45
    38.5  1124.1    47.1 1117.13    52.8 1113.35    57.1  1111.8    60.5 1111.37
      72 1111.46    81.9 1110.73   101.7 1112.27   116.6 1112.86   121.6 1114.34
   126.6 1114.64   131.5 1113.12   136.5    1111   141.5 1110.25   144.3 1110.94
   150.1 1113.27   151.4  1113.5   161.5 1112.82   178.7 1112.71     213 1112.66
     233 1113.23   245.4 1114.28   329.5 1118.62   365.4 1121.81   382.4 1122.77
#Mann= 4 ,-1,0
       0     .06       0  119.27      .1       0   136.5    .045       0
   144.3      .1       0
Bank Sta=136.5,144.3
XS Rating Curve= 0 ,0
Exp/Cntr(USF)=0,0
Exp/Cntr=0.3,0.1

Type RM Length L Ch R = 1 ,1340    ,240.1,244,232.7
XS GIS Cut Line= 2
2192005.65171101764721.3338560792191984.05979738764350.119033366
#Sta/Elev= 30
       0 1140.33    20.2 1140.14    24.2  1139.4    28.2 1136.78    35.6 1130.36
    40.2 1126.81    56.2 1116.58    60.3 1114.75    64.3 1113.46    72.3 1111.42
    76.3 1110.91    80.3 1110.85   100.3 1111.46   128.4 1111.31   136.4 1110.87
   160.4 1111.73   164.4 1111.47   166.91110.915   171.9 1110.33   177.3 1110.87
   184.5 1112.04   236.8 1114.13   272.6 1115.06   300.7 1115.03   312.7 1116.55
   316.7  1116.2   320.7 1116.43   328.7 1117.65   357.5 1119.14   371.8 1119.44
#Mann= 4 ,-1,0
       0     .06       0     100      .1       0   166.9    .045       0
   177.3      .1       0
Bank Sta=166.9,177.3
XS Rating Curve= 0 ,0
Exp/Cntr(USF)=0,0
Exp/Cntr=0.3,0.1

Type RM Length L Ch R = 1 ,1096    ,146.7,154.1,161.1
XS GIS Cut Line= 3
2192169.25197963764707.2160664012192159.28648103764286.173750707
2192056.30966221764199.806096205
#Sta/Elev= 30
       0 1127.16       2    1127       6 1125.25    10.9 1121.61      18 1115.61
      22 1113.05      26 1111.09      30 1109.99    34.3 1109.54    42.1  1109.5
    54.1 1110.22    78.1 1110.46    82.1 1109.97    84.51109.256    90.1 1108.53
    94.1 1109.33    98.1 1110.45   102.1  1110.6   150.1 1110.56   234.6 1111.92
   246.1  1111.3   254.1 1112.15   294.1 1112.86   314.1 1113.81   358.1 1113.96
   421.2 1116.26   520.6 1116.35   529.6 1117.01   534.8 1118.04   555.6 1123.35
#Mann= 4 ,-1,0
       0     .07       0    84.5    .045       0    94.1      .1       0
  551.16     .07       0
Bank Sta=84.5,94.1
XS Rating Curve= 0 ,0
Exp/Cntr(USF)=0,0
Exp/Cntr=0.3,0.1

Type RM Length L Ch R = 1 ,942     ,240.7,240.7,240.3
XS GIS Cut Line= 3
2192262.82298083764732.3927222172192464.87089332764460.447153519
2192569.49455129764384.476063956
#Sta/Elev= 30
       0 1116.83       9 1116.22    20.4    1117    23.9 1115.78    29.1 1111.75
    33.9 1108.63    38.9 1107.97    44.6 1108.63    48.9 1109.72    78.8 1109.16
     212 1108.91   223.3 1108.44   243.4 1108.53   268.1 1109.44   317.9 1109.28
   322.9 1109.55   327.9 1110.63   332.1 1112.43     339 1116.24   347.8 1122.09
   351.2 1123.05   382.4 1122.68   397.9 1123.55   406.5 1124.73     417 1125.12
   432.3 1126.87   436.8 1127.79   446.5  1130.8   455.2 1134.69   468.1 1143.49
#Mann= 6 ,-1,0
       0     .05       0      20     .07       0    33.9    .045       0
    44.6     .07       0     140      .1       0     330     .07       0
Bank Sta=33.9,44.6
XS Rating Curve= 0 ,0
Exp/Cntr(USF)=0,0
Exp/Cntr=0.3,0.1

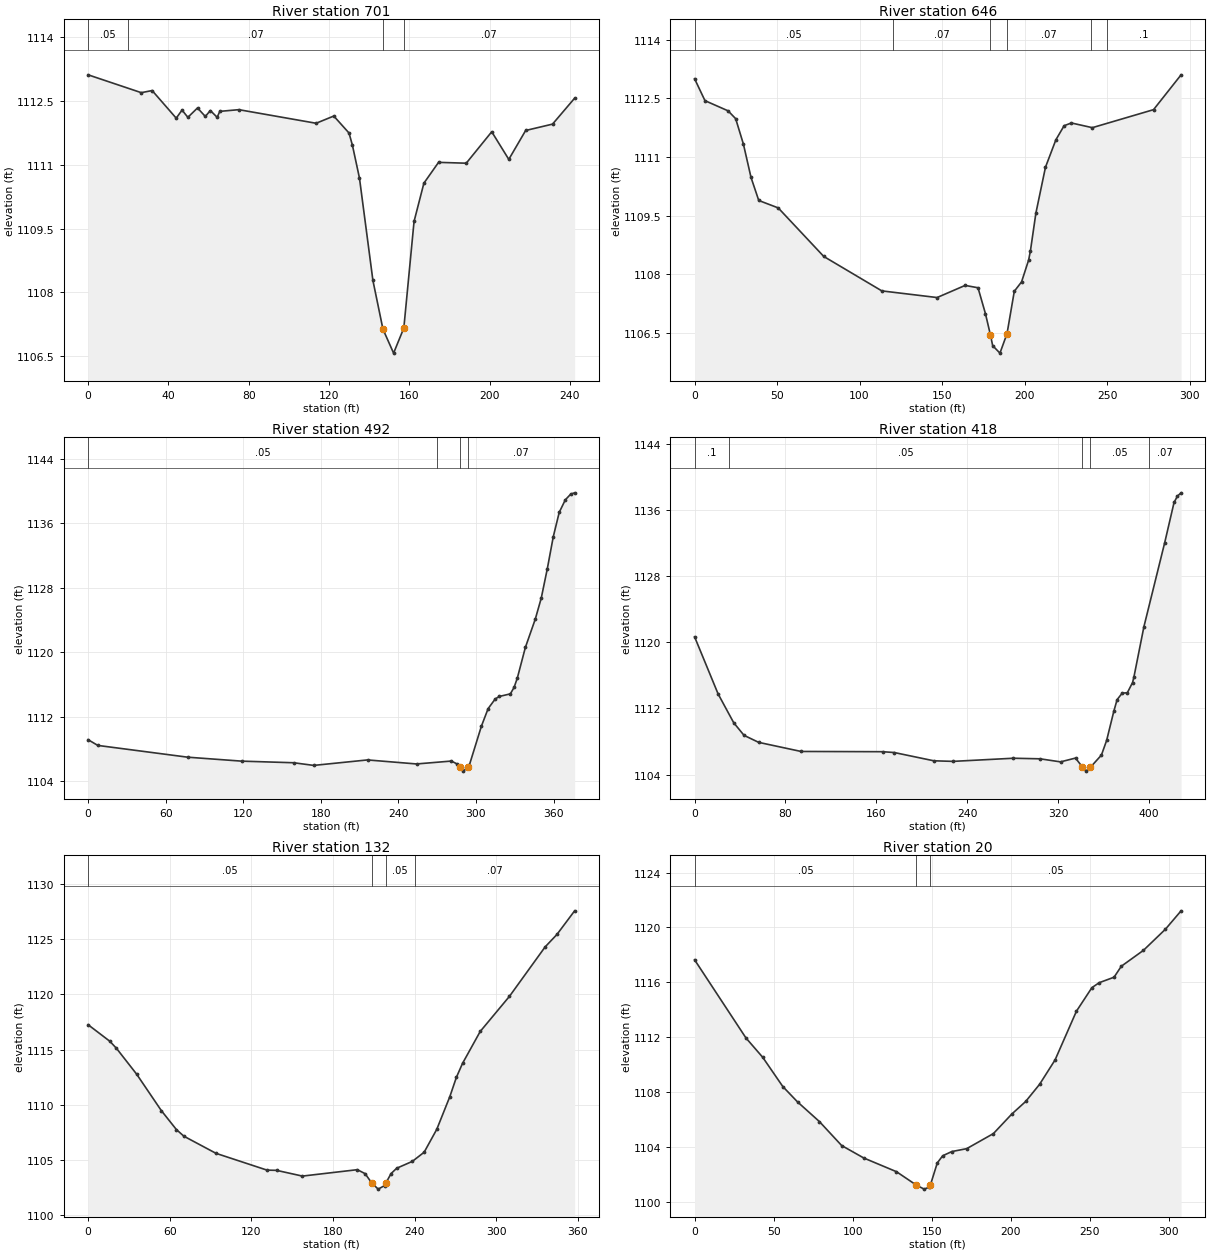
Type RM Length L Ch R = 1 ,701     ,57.7,55.5,52.4
XS GIS Cut Line= 4
2192368.52834751764734.0744290332192483.17797811 764662.41840991
2192502.63731615764638.1769808272192526.96776758764566.080873088
#Sta/Elev= 30
       0 1113.12    26.5  1112.7    31.9 1112.75    43.9  1112.1    46.8 1112.29
    49.7 1112.12    54.5 1112.34    58.4 1112.14    60.9 1112.28    64.3 1112.12
    65.6 1112.26    75.1  1112.3   113.6 1111.98   122.4 1112.15     130 1111.75
   131.7 1111.46   135.2 1110.69   141.9 1108.28   146.91107.134   152.2 1106.57
   157.3 1107.16   162.4 1109.67   167.3 1110.57   174.6 1111.06   188.4 1111.04
   201.1 1111.78   209.6 1111.13     218 1111.81   231.4 1111.96   242.4 1112.57
#Mann= 4 ,-1,0
       0     .05       0      20     .07       0   146.9    .045       0
   157.3     .07       0
Bank Sta=146.9,157.3
XS Rating Curve= 0 ,0
Exp/Cntr(USF)=0,0
Exp/Cntr=0.3,0.1

Type RM Length L Ch R = 1 ,646     ,148.5,153.5,158.3
XS GIS Cut Line= 4
2192382.79005585764781.3338097172192530.51197323764693.017670578
2192545.92187428  764658.15264072192575.02517801764578.686907603
#Sta/Elev= 30
       0    1113     6.3 1112.44    20.3 1112.18    24.9 1111.98    29.6 1111.33
    34.2 1110.48    38.9 1109.89    50.7  1109.7    78.3 1108.46   113.5 1107.58
     147 1107.41     164 1107.72   171.8 1107.66   176.3    1107   179.3 1106.46
   180.7 1106.18   185.1 1105.99   189.4 1106.49   193.8 1107.57   198.2 1107.81
   202.5 1108.37   203.6 1108.61   206.9 1109.57   212.7 1110.74     219 1111.44
     224  1111.8   228.4 1111.87   241.1 1111.75   278.2 1112.21   294.9  1113.1
#Mann= 6 ,-1,0
       0     .05       0     120     .07       0   179.3    .045       0
   189.4     .07       0  240.23     .05       0  250.23      .1       0
Bank Sta=179.3,189.4
XS Rating Curve= 0 ,0
Exp/Cntr(USF)=0,0
Exp/Cntr=0.3,0.1

Type RM Length L Ch R = 1 ,492     ,73.3,73.7,73.7
XS GIS Cut Line= 2
 2192421.7112774764857.529003562   2192746.42044764667.354072016
#Sta/Elev= 30
       0 1109.16     7.5 1108.45      77 1106.99   118.7  1106.5     159  1106.3
   174.5 1105.97   216.1 1106.65     254 1106.15     281 1106.51   285.6 1106.13
   287.5 1105.76   290.3 1105.26   293.5 1105.74   294.9 1106.02   304.2 1110.84
   309.4 1113.02   314.9 1114.22   318.1 1114.53   326.6 1114.85   329.5 1115.66
     332 1116.82   338.2 1120.61   345.9 1124.14   350.5 1126.74   355.2  1130.4
   359.8 1134.36   364.4 1137.38   369.1 1138.93   373.3 1139.64   376.3  1139.8
#Mann= 4 ,-1,0
       0     .05       0     270     .07       0   287.5    .045       0
   293.5     .07       0
Bank Sta=287.5,293.5
XS Rating Curve= 0 ,0
Exp/Cntr(USF)=0,0
Exp/Cntr=0.3,0.1

Type RM Length L Ch R = 1 ,418     ,285.9,285.9,285.9
XS GIS Cut Line= 2
 2192409.9947964764935.5815660382192785.69469853764730.257200922
#Sta/Elev= 30
       0 1120.66    20.7 1113.75    34.4 1110.27    43.5 1108.74    56.4 1107.89
    93.7 1106.79   165.5 1106.76   175.7 1106.66   210.5 1105.66   227.4 1105.59
   280.5 1105.97     304  1105.9     322 1105.53   335.2 1105.99   341.2 1104.92
   344.4 1104.41   348.2 1104.86     358 1106.35   362.6 1108.13   368.9 1111.65
   371.8 1113.06   376.3 1113.85   380.8 1113.89   385.4 1115.13   386.6  1115.8
   395.4 1121.89   413.7 1132.06   421.9 1136.91   424.9 1137.69   428.1 1138.08
#Mann= 5 ,-1,0
       0      .1       0      30     .05       0   341.2    .045       0
   348.2     .05       0     400     .07       0
Bank Sta=341.2,348.2
XS Rating Curve= 0 ,0
Exp/Cntr(USF)=0,0
Exp/Cntr=0.3,0.1

Type RM Length L Ch R = 1 ,132     ,112.3,112.3,112.3
XS GIS Cut Line= 4
2192573.74740415765157.9618714312192621.16786496765093.365262888
2192781.96065208764987.2026566272192860.22619205764954.562774225
#Sta/Elev= 30
       0 1117.26    15.9 1115.77    20.8 1115.13    35.7 1112.78    53.8 1109.49
    64.9 1107.77    70.4 1107.17      94 1105.62   131.5  1104.1   138.5 1104.08
   157.5 1103.56   197.9 1104.14   203.6 1103.78   208.4 1102.95   213.2 1102.38
   217.9  1102.7  218.78 1102.92   222.7 1103.79   226.8 1104.27   238.3 1104.89
     247 1105.72   256.3  1107.8   265.9 1110.76   270.7  1112.5   275.2 1113.76
   288.2 1116.65   309.7 1119.83   335.9  1124.3   344.6 1125.43   357.6 1127.57
#Mann= 4 ,-1,0
       0     .05       0   208.4    .045       0  218.78     .05       0
  240.13     .07       0
Bank Sta=208.4,218.78
XS Rating Curve= 0 ,0
Exp/Cntr(USF)=0,0
Exp/Cntr=0.3,0.1

Type RM Length L Ch R = 1 ,20      ,,,
XS GIS Cut Line= 2
 2192628.2644522765200.3168069552192892.62421621765042.911756626
#Sta/Elev= 30
       0 1117.64    32.5 1111.94    43.1 1110.53    55.8  1108.4    65.1 1107.28
      79 1105.84      93  1104.1     107 1103.19   127.7 1102.19   140.3 1101.21
   145.2 1100.92   148.1 1101.05  149.17 1101.23   153.5 1102.83   156.9 1103.35
   162.7 1103.66   172.1 1103.87     189 1104.97   200.6 1106.39   209.4 1107.31
   218.2 1108.56     228 1110.34   241.5 1113.89   251.3 1115.61   255.9 1115.97
   265.3 1116.37   269.9 1117.17   283.9 1118.33   297.8 1119.87   307.7 1121.21
#Mann= 3 ,-1,0
       0     .05       0   140.3    .045       0  149.17     .05       0
Bank Sta=140.3,149.17
XS Rating Curve= 0 ,0
Exp/Cntr(USF)=0,0
Exp/Cntr=0.3,0.1
LCMann Table=0

Chan Stop Cuts=-1
Use User Specified Reach Order=0
Composite Channel Slope=5